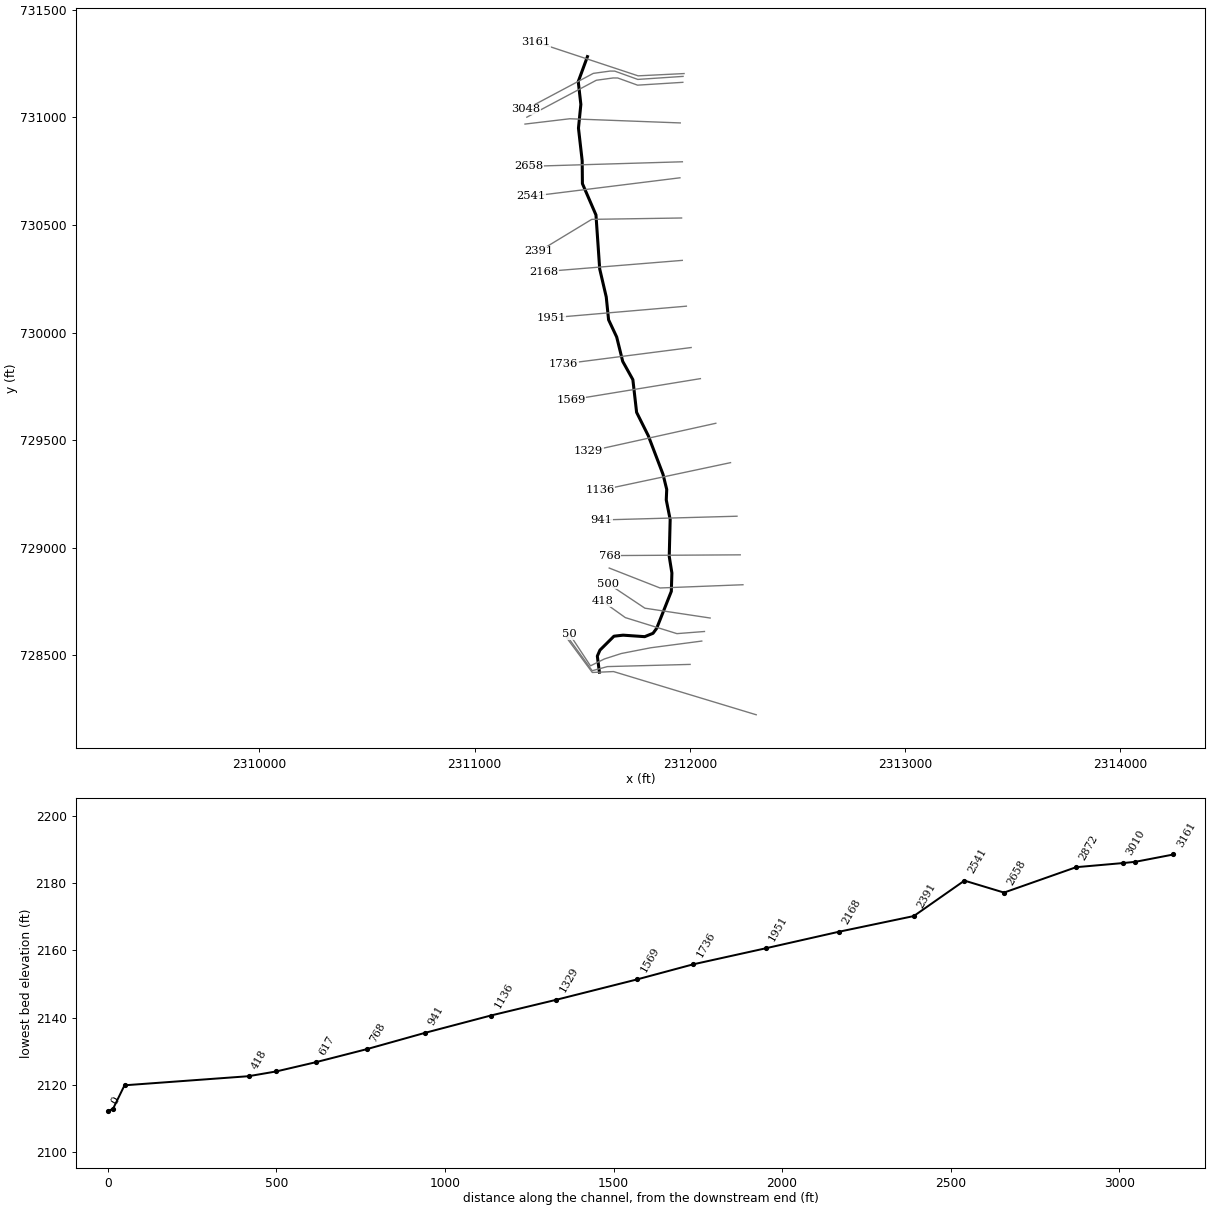
--- BEARLCKRN.prj (project) ---

Proj Title=BEARLCKRN
Current Plan=p01
Default Exp/Contr=0,0
English Units
Geom File=g01
Flow File=f01
Plan File=p01
BEGIN DESCRIPTION:
----------MODEL BY WOOD PLC 2022----------
AFH study
Randolph County, WV
HEC-RAS Version: RAS 6.2
Vertical Datum: NAVD88
Projection: NAD 1983 StatePlane West Virginia S FIPS 4702 (US Feet)
Terrain: 1-meter LIDAR (FEMA Region III 3DEP collected 2016-2018)
Land Use: 2019 NLCD
Hydrologic Method:
WV SIR2010-5033 regression equations
Additional Model Notes:
KWSE tie-in to LOGLCKRN
END DESCRIPTION:
DSS Export Rating Curves= 0
DSS Export Rating Curve Sorted= 0
DSS Export Volume Flow Curves= 0
DXF OffsetX= 0
DXF OffsetY= 0
DXF ScaleX= 0
DXF ScaleY= 0

--- BEARLCKRN.p01 (plan) ---

Plan Title=Floodplain
Program Version=6.20
Short Identifier=Floodplain
Geom File=g01
Flow File=f01
Subcritical Flow
K Sum by GR= 0
Std Step Tol= 0.01
Critical Tol= 0.01
Num of Std Step Trials= 20
Max Error Tol= 0.3
Flow Tol Ratio= 0.001
Split Flow NTrial= 30
Split Flow Tol= 0.02
Split Flow Ratio= 0.02
Log Output Level= 0
Friction Slope Method= 1
Unsteady Friction Slope Method= 2
Unsteady Bridges Friction Slope Method= 1
Parabolic Critical Depth
Global Vel Dist= 0 , 0 , 0
Global Log Level= 0
CheckData=True
Encroach Param=-1 ,0,0, 0
Mapping Interval=1HOUR
Computation Time Step Use Courant=        0
Computation Time Step Use Time Series=    0
Computation Time Step Count To Double=0
Computation Time Step Max Doubling=0
Computation Time Step Max Halving=0
Computation Time Step Residence Courant=0
Run HTab= 0
Run UNet= 0
Run Sediment= 0
Run PostProcess= 0
Run WQNet= 0
Run RASMapper=-1
UNET Theta= 0
UNET Theta Warmup= 0
UNET ZTol= 0
UNET ZSATol= 0
UNET MxIter= 0
UNET Max Iter WO Improvement= 0
UNET MaxInSteps= 0
UNET DtIC= 0
UNET DtMin= 0
UNET MaxCRTS= 0
UNET WFStab= 0
UNET SFStab= 0
UNET WFX= 1
UNET SFX= 1
UNET Gravity=32.174
UNET 1D Methodology=Finite Difference
UNET DSS MLevel= 1
UNET Pardiso=0
UNET DZMax Abort= 0
UNET Use Existing IB Tables= 0
UNET Froude Reduction=False
UNET Froude Limit= 0
UNET Froude Power= 0
UNET D1 Cores= 0
UNET WindReference=Eulerian
UNET WindDragFormulation=Hsu (1988)
UNET D2 Coriolis=0
UNET D2 Cores= 0
UNET D2 Theta= 1
UNET D2 Theta Warmup= 1
UNET D2 Z Tol= 0.01
UNET D2 Volume Tol= 0.01
UNET D2 Max Iterations= 20
UNET D2 Equation= 0
UNET D2 RampUpFraction=0.1
UNET D2 TimeSlices= 1
UNET D2 Turbulence Formulation=Non-Conservative (original)
UNET D2 Eddy Viscosity=0.3
UNET D2 Transverse Eddy Viscosity=0.1
UNET D2 Smagorinsky Mixing=0
UNET D2 BCVolumeCheck=0
UNET D2 Cores=0
UNET D2 SolverType=PARDISO (Direct)
UNET D2 Minimum Iterations= 2147483647
UNET D2 Maximum Iterations= 2147483647
UNET D2 Restart Number= 10
UNET D2 Relaxation Coeff=1.3
UNET D2 SOR Precondition Iterations= 10
UNET D2 ILUT Maximum Fill= 8
UNET D2 ILUT Tolerance=1E-08
UNET D1D2 MaxIter= 0
UNET D1D2 ZTol=0.01
UNET D1D2 QTol=0.1
UNET D1D2 MinQTol=1
Write IC File= 0
Write IC File at Fixed DateTime=0
Write IC File at Sim End=0
Echo Input=False
Echo Parameters=False
Echo Output=False
Write Detailed= 0
HDF Write Warmup=0
HDF Write Time Slices=0
HDF Flush=0
HDF Compression= 1
HDF Chunk Size= 1
HDF Spatial Parts= 1
HDF Use Max Rows=0
HDF Fixed Rows= 1
Calibration Method= 0
Calibration Iterations= 20
Calibration Max Change=0.05
Calibration Tolerance=0.2
Calibration Maximum=1.5
Calibration Minimum=0.5
Calibration Optimization Method= 1
WQ AD Non Conservative
WQ ULTIMATE=-1
WQ Max Comp Step=1HOUR
WQ Output Interval=15MIN
WQ Output Selected Increments= 0
WQ Output face flow=0
WQ Output face velocity=0
WQ Output face area=0
WQ Output face dispersion=0
WQ Output cell volume=0
WQ Output cell surface area=0
WQ Output cell continuity=0
WQ Output cumulative cell continuity=0
WQ Output face conc=0
WQ Output face dconc_dx=0
WQ Output face courant=0
WQ Output face peclet=0
WQ Output face adv mass=0
WQ Output face disp mass=0
WQ Output cell mass=0
WQ Output cell source sink temp=0
WQ Output nsm pathways=0
WQ Output nsm derived pathways=0
WQ Create Restart=0
WQ Fixed Restart=0
WQ System Summary=0
WQ Write To DSS=0
Sorting and Armoring Iterations= 10
XS Update Threshold= 0.02
Bed Roughness Predictor= 0
Hydraulics Update Threshold= 0.02
Energy Slope Method= 1
Volume Change Method= 1
Sediment Retention Method= 0
Sediment TS Multiplier= 1
Warm Up Method= 0
XS Weighting Method= 0
Number of US Weighted Cross Sections= 1
Number of DS Weighted Cross Sections= 1
Upstream XS Weight=0
Main XS Weight=1
Downstream XS Weight=0
Number of DS XS's Weighted with US Boundary= 1
Upstream Boundary Weight= 1
Weight of XSs Associated with US Boundary= 0
Number of US XS's Weighted with DS Boundary= 1
Downstream Boundary Weight= 0.5
Weight of XSs Associated with DS Boundary= 0.5
Percentile Method= 0
Sediment Output Level= 3
Mass or Volume Output= 0
Output Increment Type= 1
Profile and TS Output Increment= 1
Transport Output Increment 1
XS Output Flag= 0
XS Output Increment= 10
Read HDF5 Sediment Hotstart= 0
Sediment Hotstart Type= 0
Write Gradation File= 0
Read Gradation Hotstart= 0
Write HDF5 File= 1
Write Binary Output= 1
Write DSS Sediment File= 0
DSS Sediment Output Type= 1
SV Curve= 0
Specific Gage Flag= 0
Subcell Erosion Methods= 0
Subcell Deposition Methods= 0
Advection Scheme= 1
Matrix Solver= 0
Implicit Weighting Factor= 1
Maximum Outer Loop Convergence Iterations= 5
Convergence Maximum Absolute= 0.001
Convergence RMSE= 0.0001
Grain Fractions Max Abs Error= 0.001
Max Subgrid Regions= 1
Max Subgrid Length Scale= 3.402823E+38
Initial Layer Thickness= 3.402823E+38
Min Layer Thickness= 3.402823E+38
Max Layer Thickness= 3.402823E+38
Number of Layers= 5

--- BEARLCKRN.f01 (steady flow) ---

Flow Title=Flow
Program Version=6.20
Number of Profiles= 1
Profile Names=P100yr
River Rch & RM=BEARLCKRN,Main            ,3161
     354
River Rch & RM=BEARLCKRN,Main            ,0
     599
Boundary for River Rch & Prof#=BEARLCKRN,Main            , 1
Up Type= 0
Dn Type= 1
Dn Known WS=2116.31
DSS Import GetInterval= 0
DSS Import GetPeak= 0
DSS Import FillOption= 0

--- BEARLCKRN.g01 (geometry) ---

Geom Title=Geometry
Program Version=6.20

River Reach=BEARLCKRN       ,Main
Reach XY= 30
     2311523.757 731281.549000012311481.09699216731165.654219326
2311493.20199999731059.6739999952311482.09099999730949.256999999
2311499.36499999730797.868000001      2311500.45730691.531000003
2311563.38400002730546.131999999     2311580.745730295.481000006
2311611.19852747730164.9853372122311622.00160684730059.170559839
2311659.65498985729979.1489878092311687.58998782729866.024985771
     2311734.825729781.158000007     2311752.186729629.247999996
2311806.44000003729520.7409999972311874.79900001729341.704999998
2311892.16000001729271.1750000122311889.98999999729222.347000003
2311908.13200001729131.5919999932311903.79199998728959.891000003
2311916.11800003728883.1539999992311913.51399998728797.825000003
2311845.37199999728625.9500000182311828.44500004 728602.94600001
2311789.81600003 728587.321000012311689.55600002728594.266000018
2311647.02099998728589.4909999972311581.91700001 728524.82100001
     2311569.764728497.0429999982311579.32816401728422.389182627

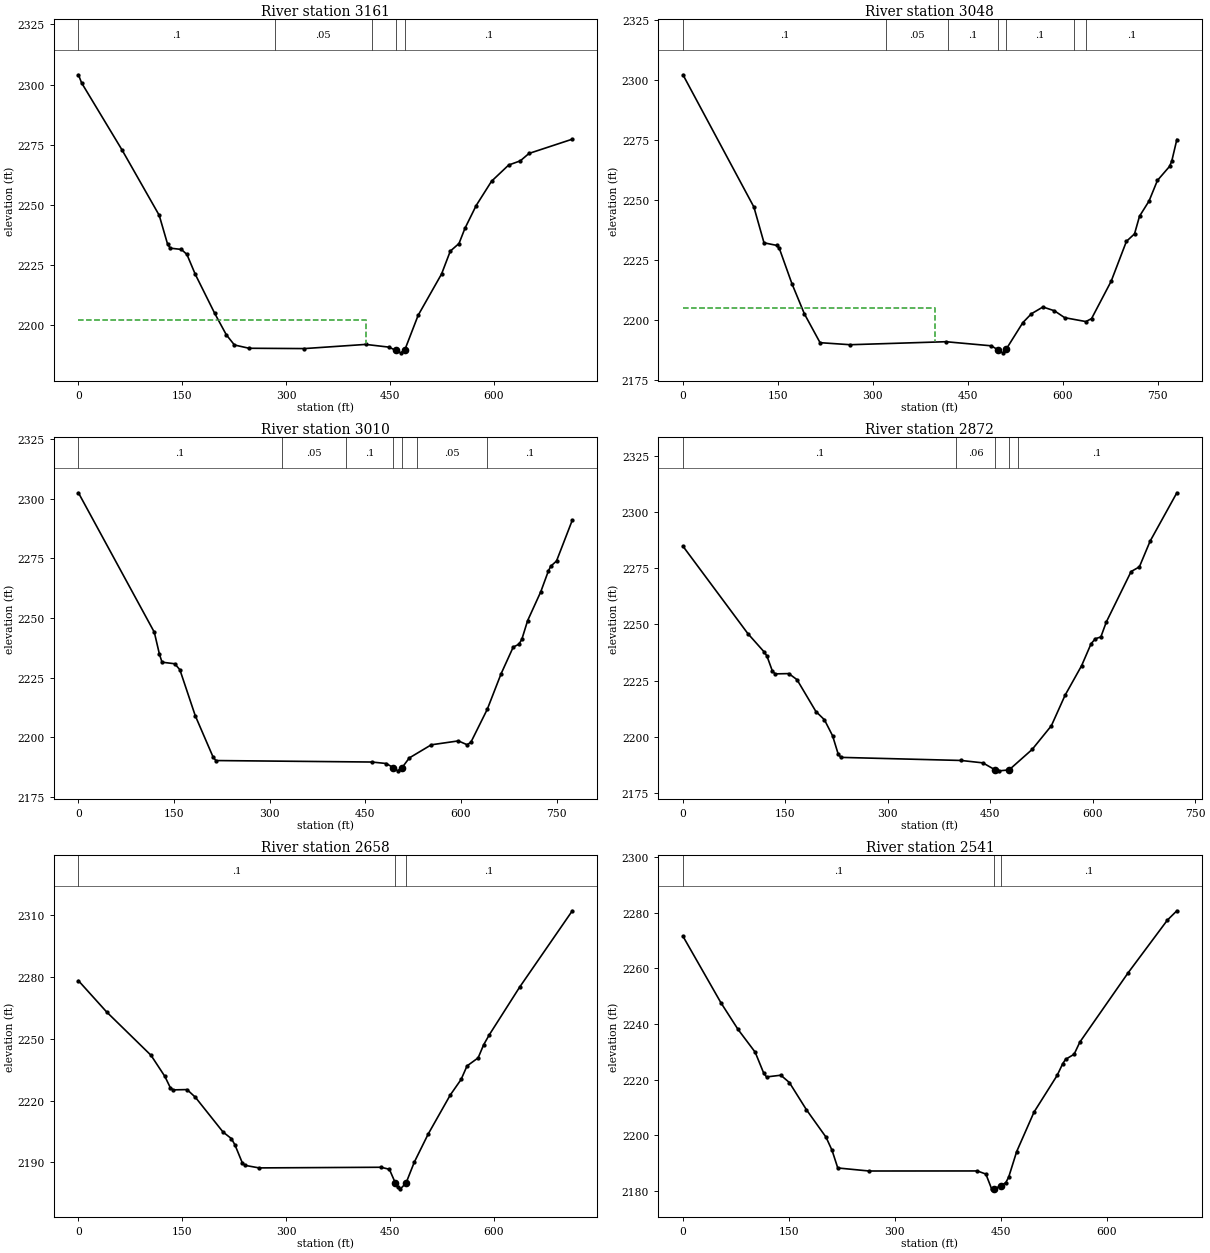
Type RM Length L Ch R = 1 ,3161    ,112.9,112.9,112.9
BEGIN DESCRIPTION:
Structure XS 4
END DESCRIPTION:
XS GIS Cut Line= 3
2311972.73102847731202.8265738562311759.29087056731192.242764373
2311284.78341206731349.235938374
#Sta/Elev= 30
       0 2304.04     4.6 2300.67    63.2 2272.72   116.7 2245.67   128.7 2233.78
   132.7 2232.01   148.7 2231.49   156.7 2229.43   168.8 2221.16   196.8 2204.98
   213.7    2196   225.4 2191.79   246.5 2190.43   326.5  2190.3     415 2192.03
   448.7  2190.9   458.6 2189.52   465.6 2188.53   471.4 2189.68   490.8 2204.14
   524.6 2221.29   537.2 2230.78   549.8 2233.95   558.3 2240.21   574.6 2249.72
   596.8 2259.82   621.5 2266.54   638.3 2268.28   650.9 2271.36   713.5 2277.29
#Mann= 5, -1 ,  0
       0     0.1       0   283.7    0.05       0   423.7     0.1       0
   458.6   0.045       0   471.4     0.1       0
#XS Ineff= 2 , 0
          414.73 2202.21
Permanent Ineff=
       F       F
Bank Sta=458.6,471.4
XS Rating Curve= 0 ,0
Exp/Cntr(USF)=0,0
Exp/Cntr=0.3,0.1

Type RM Length L Ch R = 1 ,3048    ,37.6,37.6,37.6
BEGIN DESCRIPTION:
Structure XS 3
END DESCRIPTION:
XS GIS Cut Line= 6
2311967.99649939731189.6978890512311757.77519958731175.626805483
 2311650.6099375731214.2111711442311629.36545771731214.420677705
2311550.97059062731203.6936845292311237.10715187731036.595970286
#Sta/Elev= 30
       0 2302.13   112.1 2247.07   128.1 2232.16   148.2 2231.09   152.2 2229.91
   172.2 2215.16   191.9 2202.59   216.7 2190.58   264.2 2189.73   415.7 2190.98
   487.4 2189.27   497.4 2187.66   505.5 2186.35  510.682187.802   537.2 2198.94
   550.7 2202.62   568.9 2205.44     587 2203.87   603.3 2200.99   636.8 2199.37
   645.8 2200.61   676.8 2216.19   700.9 2232.78   713.7 2235.89   721.6 2243.25
   736.6 2249.55   749.9 2258.15     769 2263.96   772.6 2266.26   780.6 2275.18
#Mann= 7, -1 ,  0
       0     0.1       0  320.53    0.05       0  418.72     0.1       0
   497.4   0.045       0  510.68     0.1       0  617.28    0.05       0
  637.28     0.1       0
#XS Ineff= 2 , 0
          397.98 2204.86
Permanent Ineff=
       F       F
Bank Sta=497.4,510.68
XS Rating Curve= 0 ,0
Exp/Cntr(USF)=0,0
Exp/Cntr=0.3,0.1

Type RM Length L Ch R = 1 ,3010    ,138.1,138.1,138.1
BEGIN DESCRIPTION:
Structure XS 2
END DESCRIPTION:
XS GIS Cut Line= 6
2311966.98117138731162.1383718212311756.75987158731148.949992783
2311664.60058652731182.2381312592311643.35610672731182.447637821
2311564.96123964731171.7206446442311242.27075558731000.209407747
#Sta/Elev= 30
       0 2302.42     119 2244.02   127.1 2234.74   131.1 2231.47   151.1 2230.81
   159.1  2228.3   183.2 2209.07   211.2 2191.73   215.5 2190.28   460.1 2189.66
   482.7 2189.04     494 2187.26   500.8 2185.97  507.39 2187.27   518.9 2191.38
   553.3 2196.87   595.8 2198.51   609.5  2196.9   615.5 2197.97   641.1 2211.73
   662.8 2226.63   681.8 2237.79   690.8 2239.01   695.4 2241.11   704.4 2248.88
     725 2260.95   736.8 2269.56   740.6 2271.64   749.7 2273.84   774.5 2290.98
#Mann= 7, -1 ,  0
       0     0.1       0  318.62    0.05       0     419     0.1       0
     494   0.045       0  507.39     0.1       0  531.31    0.05       0
  641.31     0.1       0
Bank Sta=494,507.39
XS Rating Curve= 0 ,0
Exp/Cntr(USF)=0,0
Exp/Cntr=0.3,0.1

Type RM Length L Ch R = 1 ,2872    ,213.9,213.9,213.9
BEGIN DESCRIPTION:
Structure XS 1
END DESCRIPTION:
XS GIS Cut Line= 3
  2311955.091346730973.5107017182311441.77658606730992.914352438
2311233.62833289730968.218796977
#Sta/Elev= 30
       0 2284.83      95 2245.91     119  2237.7     123 2235.89     131 2229.17
     135 2227.95     155 2228.08     167 2225.38   194.7 2211.18   207.1 2207.53
   219.1 2200.39   227.1 2192.45   231.1 2190.75   407.5 2189.37   439.2  2188.3
   457.6  2185.1   463.2 2184.75   477.6 2185.17   511.3 2194.26   539.5 2204.83
   559.6 2218.44   583.8  2231.6   597.7  2241.4   603.9  2243.6     612 2244.42
     620 2251.08   656.3 2273.55   668.4 2275.63   684.1 2287.07   723.3 2308.64
#Mann= 5, -1 ,  0
       0     0.1       0     400    0.06       0   457.6   0.045       0
   477.6    0.06       0     490     0.1       0
Bank Sta=457.6,477.6
XS Rating Curve= 0 ,0
Exp/Cntr(USF)=0,0
Exp/Cntr=0.3,0.1

Type RM Length L Ch R = 1 ,2658    ,117.4,117.4,117.4
XS GIS Cut Line= 2
2311964.88080875730793.0665974582311252.23763688730771.898978491
#Sta/Elev= 30
       0 2278.22    40.7 2263.05   104.8 2241.99   124.8 2231.75   132.8 2226.18
   136.8 2225.22   156.8 2225.36   168.8 2221.65   208.8 2204.75   220.8 2201.58
     226 2198.49   236.8 2189.62   240.8 2188.57   260.8 2187.35   436.9 2187.66
   448.9 2186.68  457.262180.233   460.9 2177.89   464.9 2177.19   472.9 2179.97
   484.9 2190.16   504.9 2203.77   536.9 2222.79   552.4 2230.26     561 2236.84
     577 2240.74     585 2247.11     593 2251.88     637 2275.11     713 2312.14
#Mann= 3, -1 ,  0
       0     0.1       0  457.26   0.045       0   472.9     0.1       0
Bank Sta=457.26,472.9
XS Rating Curve= 0 ,0
Exp/Cntr(USF)=0,0
Exp/Cntr=0.3,0.1

Type RM Length L Ch R = 1 ,2541    ,150.2,150.2,150.2
BEGIN DESCRIPTION:
Structure
END DESCRIPTION:
XS GIS Cut Line= 2
  2311953.596186 730718.660060282311259.94778346730632.551982724
#Sta/Elev= 30
       0 2271.53    53.8  2247.6      78 2238.03   102.2 2229.86   114.3 2222.33
   118.3 2220.97   138.5 2221.59   150.6 2218.96   174.8 2209.16   202.4 2199.35
     211 2194.59   219.1 2188.25   263.4 2187.16   416.6 2187.18   428.7 2186.06
   436.7 2180.82     440 2180.75     4502181.814   456.9 2183.01   460.9  2184.9
   472.3 2194.15   496.9 2208.36   529.5 2221.49   537.5 2225.76   541.5 2227.29
   553.6 2229.13   561.7 2233.49   630.2 2258.46   685.6 2277.34     699 2280.69
#Mann= 3, -1 ,  0
       0     0.1       0     440   0.045       0     450     0.1       0
Bank Sta=440,450
XS Rating Curve= 0 ,0
Exp/Cntr(USF)=0,0
Exp/Cntr=0.3,0.1

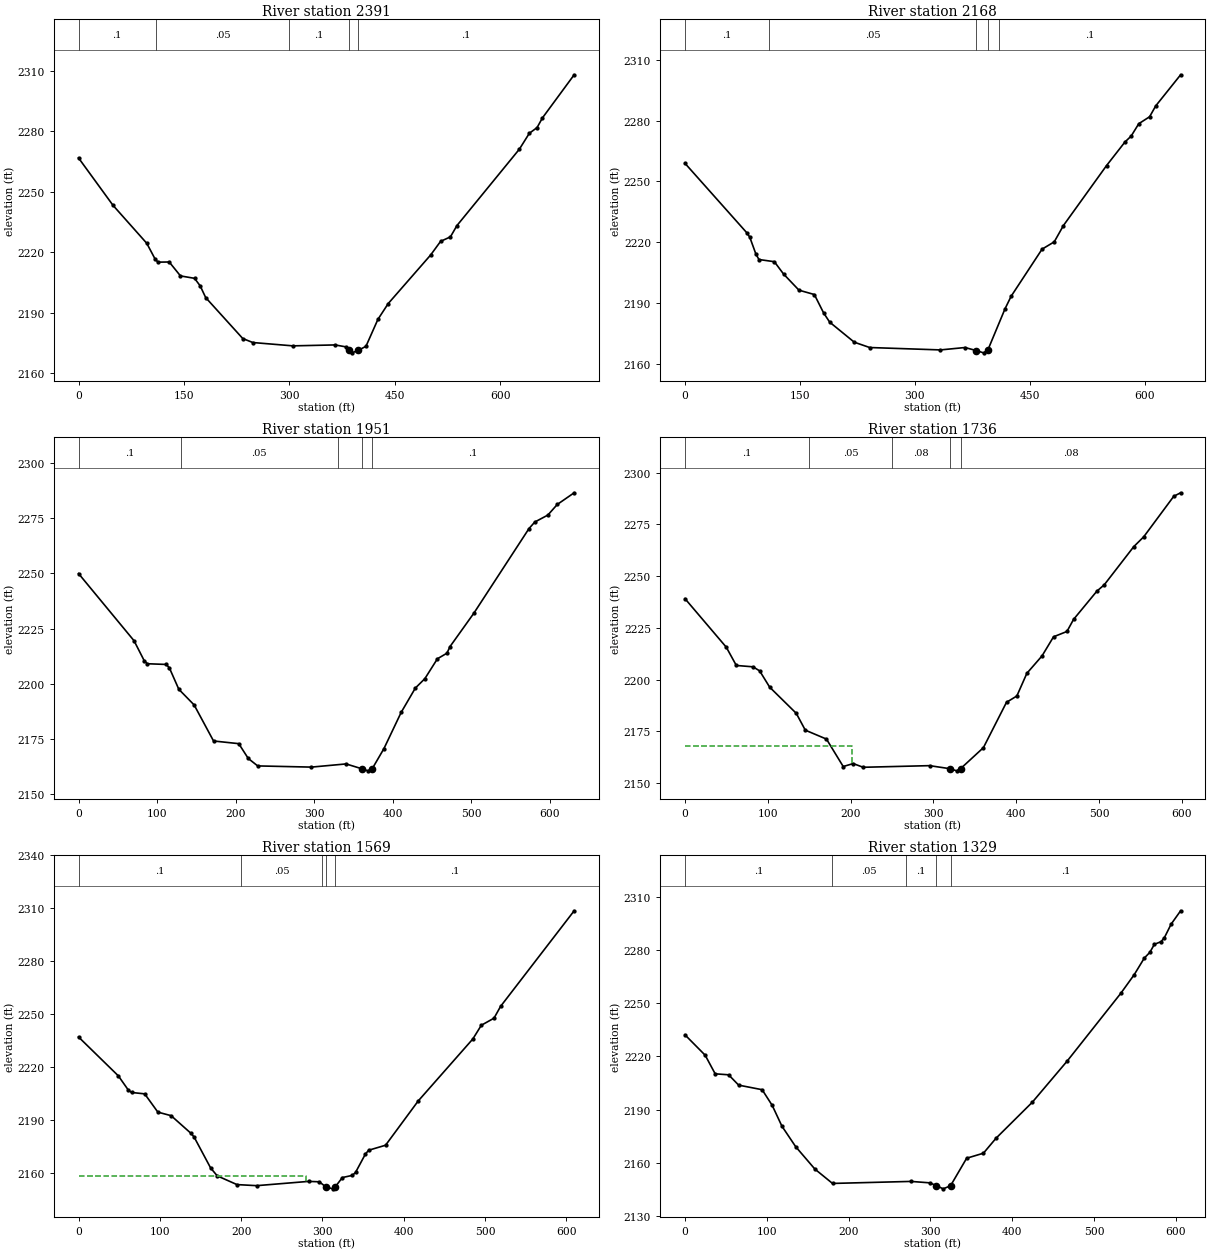
Type RM Length L Ch R = 1 ,2391    ,223,223,223
XS GIS Cut Line= 3
2311961.22052346730531.9715461662311543.68923935730525.621260476
2311297.61566886730376.389546762
#Sta/Elev= 30
       0 2266.83    49.1 2243.32    97.1 2224.52   109.1 2216.63   113.1 2215.16
   129.1 2215.24   145.1 2208.33   165.1 2207.14   173.1 2203.43     181 2197.59
   233.8 2177.28   248.1 2175.31   305.1 2173.66   365.1 2174.12   381.1 2173.13
  384.492171.393   389.1  2170.2   397.8 2171.37   409.1 2173.44   426.1  2186.8
   440.8 2194.64   501.2 2218.73   515.3 2225.46   529.3 2227.69   538.6  2233.3
   627.5  2271.2   641.6 2279.04   652.6 2281.86   660.3 2286.69   705.4 2308.04
#Mann= 5, -1 ,  0
       0     0.1       0     110    0.05       0     300     0.1       0
  384.49   0.045       0   397.8     0.1       0
Bank Sta=384.49,397.8
XS Rating Curve= 0 ,0
Exp/Cntr(USF)=0,0
Exp/Cntr=0.3,0.1

Type RM Length L Ch R = 1 ,2168    ,216.8,216.8,216.8
XS GIS Cut Line= 2
2311964.39566631730335.1126897772311319.84166877730282.722832835
#Sta/Elev= 30
       0 2258.92    80.5 2224.76    84.5 2222.56    92.5 2214.22    96.5 2211.51
   116.6 2210.43   128.6 2204.37   148.7  2196.4   168.8 2194.25   180.8 2185.24
   188.8 2180.64   220.9 2170.75     241 2168.13   333.3 2166.95   365.4 2168.13
  380.162166.615   389.5 2165.51  394.972166.723   417.6 2187.24   425.6 2193.43
   465.9 2216.61   481.8 2220.22   493.8 2228.27     550 2257.79   574.1 2269.45
   582.1 2272.32   592.1 2278.45   606.2 2281.87   614.2 2287.22   646.7 2302.56
#Mann= 5, -1 ,  0
       0     0.1       0     110    0.05       0  380.16   0.045       0
  394.97    0.05       0     410     0.1       0
Bank Sta=380.16,394.97
XS Rating Curve= 0 ,0
Exp/Cntr(USF)=0,0
Exp/Cntr=0.3,0.1

Type RM Length L Ch R = 1 ,1951    ,214.5,214.5,214.5
XS GIS Cut Line= 2
2311983.44652338730122.3781191642311354.76824007730068.400690799
#Sta/Elev= 30
       0 2249.95    70.7  2219.5    83.6  2210.5    87.6 2209.09   111.7 2208.77
   115.7  2207.2   127.7 2197.52   147.2 2190.43   171.9 2174.11     204  2172.9
   216.1 2166.19   228.1 2162.82   296.5 2162.28   340.6 2163.72   360.6 2161.54
   368.6 2160.59   373.9 2161.54   388.8 2170.64   410.8 2187.09   428.8 2198.07
   440.9 2202.32   456.9 2211.34     469 2213.86     473 2216.89   503.3 2231.98
   573.5 2270.31   580.9 2273.27   597.5 2276.41   609.5 2281.22     631 2286.51
#Mann= 5, -1 ,  0
       0     0.1       0     130    0.05       0     330     0.1       0
   360.6   0.045       0   373.9     0.1       0
Bank Sta=360.6,373.9
XS Rating Curve= 0 ,0
Exp/Cntr(USF)=0,0
Exp/Cntr=0.3,0.1

Type RM Length L Ch R = 1 ,1736    ,167.2,167.2,167.2
XS GIS Cut Line= 2
2312005.67252329729930.2819770432311411.92081128729854.078548763
#Sta/Elev= 30
       0 2239.11    49.9 2215.62      62  2206.8    82.2 2206.14    90.2 2204.17
   102.3 2196.29   134.4 2183.65   145.3 2175.51   170.9 2171.18   191.1 2157.92
   203.2 2159.34   215.2 2157.55   295.4 2158.34   320.1 2156.86   328.2 2155.83
  332.872156.896   360.4 2167.04   388.3 2188.98   400.8 2192.03   412.9    2203
   431.2 2211.41   445.1 2220.66   461.3 2223.24   469.3 2229.08   497.5 2242.76
   506.3 2245.78     542 2264.27     554 2269.01   590.3 2288.62   598.6 2290.32
#Mann= 5, -1 ,  0
       0     0.1       0     150    0.05       0     250    0.08       0
   320.1   0.045       0  332.87    0.08       0
#XS Ineff= 2 , 0
          201.13 2167.77
Permanent Ineff=
       F       F
Bank Sta=320.1,332.87
XS Rating Curve= 0 ,0
Exp/Cntr(USF)=0,0
Exp/Cntr=0.3,0.1

Type RM Length L Ch R = 1 ,1569    ,239.9,239.9,239.9
XS GIS Cut Line= 2
 2312048.5369517729785.8129775962311446.84738257729687.383549402
#Sta/Elev= 30
       0 2237.24      49 2215.23    61.2 2207.24    65.2 2205.84    81.4 2205.05
    97.6 2194.72   113.9 2192.71   138.2 2182.78   142.2 2180.62   162.5 2163.15
   170.6 2158.68   194.9 2153.72   219.2 2153.12     283 2155.53   296.2 2155.31
   303.9 2152.53   312.5 2151.32  315.742152.426   324.6 2157.71   336.8 2158.93
   340.8 2160.63     353 2171.08     357 2173.17   377.7 2175.99   417.8    2201
   485.1 2236.13   495.5 2243.86   511.1 2247.87   519.2 2254.55   609.7 2308.62
#Mann= 5, -1 ,  0
       0     0.1       0     200    0.05       0     300     0.1       0
   303.9   0.045       0  315.74     0.1       0
#XS Ineff= 2 , 0
          279.47 2158.73
Permanent Ineff=
       F       F
Bank Sta=303.9,315.74
XS Rating Curve= 0 ,0
Exp/Cntr(USF)=0,0
Exp/Cntr=0.3,0.1

Type RM Length L Ch R = 1 ,1329    ,193.1,193.1,193.1
XS GIS Cut Line= 2
2312120.24596528729578.4523362482311528.84544654729447.672965177
#Sta/Elev= 30
       0 2232.21    24.7 2220.68    36.9 2210.19    53.3 2209.64    65.6 2203.81
    94.3 2201.22   106.6 2192.37   118.5  2180.6   135.3 2169.04   158.8 2156.38
   180.3  2148.3   276.2 2149.44   299.1 2148.64   307.3 2147.05   315.5 2145.25
   324.5 2146.97   344.2 2162.53   364.7 2165.37   380.2 2173.87   424.5 2194.18
   467.1 2217.42   532.6 2255.66     549 2266.19   561.3 2275.54   568.1 2278.79
   573.6  2283.3   581.8 2284.82   585.9 2287.11   594.1 2294.72   605.7 2302.25
#Mann= 5, -1 ,  0
       0     0.1       0     180    0.05       0     270     0.1       0
   307.3   0.045       0   324.5     0.1       0
Bank Sta=307.3,324.5
XS Rating Curve= 0 ,0
Exp/Cntr(USF)=0,0
Exp/Cntr=0.3,0.1

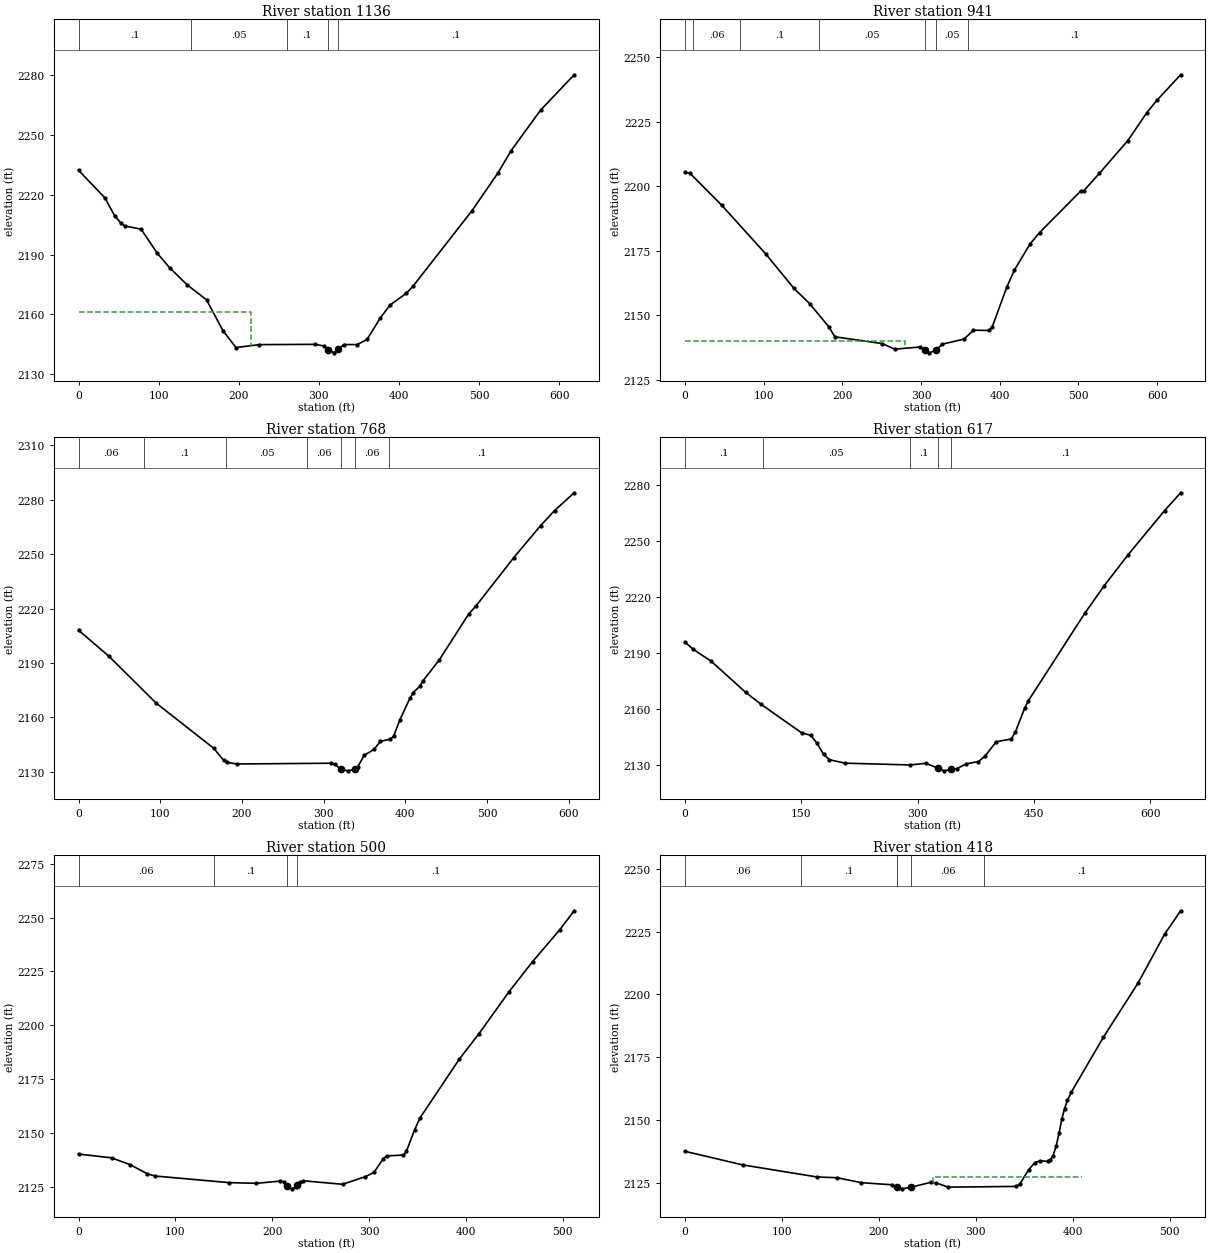
Type RM Length L Ch R = 1 ,1136    ,195.2,195.2,195.2
XS GIS Cut Line= 2
2312188.52899973729395.5926846632311583.24040619729267.127992726
#Sta/Elev= 30
       0 2232.36    33.1  2218.4    45.3 2209.33    53.5 2205.61    57.6 2204.37
    78.1 2202.75    98.5 2190.57   113.6 2183.46   135.3 2174.89   159.8 2167.24
   180.3 2151.75   196.6 2143.25   225.7 2144.72   294.8 2144.86     307 2144.02
   311.1 2142.17   319.3 2140.59   324.3 2142.33   331.6 2144.78   347.9 2144.72
   360.2 2147.33   376.6 2158.02   388.8 2164.58   409.3 2170.51   417.8 2174.17
   491.1 2211.95   523.8 2231.08   540.1  2242.2   576.9 2262.58   618.8 2280.34
#Mann= 5, -1 ,  0
       0     0.1       0     140    0.05       0     260     0.1       0
   311.1   0.045       0   324.3     0.1       0
#XS Ineff= 2 , 0
          215.31 2160.97
Permanent Ineff=
       F       F
Bank Sta=311.1,324.3
XS Rating Curve= 0 ,0
Exp/Cntr(USF)=0,0
Exp/Cntr=0.3,0.1

Type RM Length L Ch R = 1 ,941     ,173,173,173
XS GIS Cut Line= 2
2312218.61982847729146.7646777592311589.02710403729129.404584254
#Sta/Elev= 30
       0  2205.3     6.4 2204.98    46.5 2192.67   102.5 2173.78   138.5 2160.39
   158.5 2154.46   182.5 2145.61   190.5 2141.63   250.5 2139.03   266.5 2136.86
   298.6 2137.68  305.522136.448   310.6 2135.43   318.6 2136.42   327.1  2138.8
   354.6 2140.75   366.6  2144.2   386.6 2144.09   390.6 2145.63   408.9 2160.87
   418.6  2167.5   438.6 2177.67   450.6 2182.02   502.6 2198.03   506.6 2198.17
   526.6 2204.97   562.7 2217.64   586.7 2228.42   599.7 2233.26   629.8 2243.14
#Mann= 7, -1 ,  0
       0     0.1       0      10    0.06       0      70     0.1       0
     170    0.05       0  305.52   0.045       0   318.6    0.05       0
     360     0.1       0
#XS Ineff= 2 , 0
             280    2140
Permanent Ineff=
       F       F
Bank Sta=305.52,318.6
XS Rating Curve= 0 ,0
Exp/Cntr(USF)=0,0
Exp/Cntr=0.3,0.1

Type RM Length L Ch R = 1 ,768     ,151,151,151
XS GIS Cut Line= 2
2312233.66524285728967.3770448752311627.21930974728963.905026174
#Sta/Elev= 30
       0  2208.1    37.5 2193.62    95.1 2167.89   165.5 2142.98   177.5 2136.45
   181.5 2135.27   193.5 2134.35   309.5 2134.77   313.5 2134.19   321.1 2131.43
   329.2 2130.57  338.76 2131.46   341.5 2132.67   349.5 2139.04   361.5 2142.41
   369.5 2146.85   381.5 2148.03   385.5 2149.62   393.4 2158.82   405.5 2170.58
   409.5  2173.7   417.5 2177.13   421.7 2180.35   441.2 2191.56   477.5 2217.06
   486.1 2221.34   532.6 2248.12   565.5 2265.81   582.6 2274.09   606.5 2283.87
#Mann= 7, -1 ,  0
       0    0.06       0      80     0.1       0     180    0.05       0
     280    0.06       0   321.1   0.045       0  338.76    0.06       0
     380     0.1       0
Bank Sta=321.1,338.76
XS Rating Curve= 0 ,0
Exp/Cntr(USF)=0,0
Exp/Cntr=0.3,0.1

Type RM Length L Ch R = 1 ,617     ,116.5,116.5,116.5
XS GIS Cut Line= 3
2312246.39597808728828.4962968352311861.00190227728813.450882464
2311624.90463061728906.038047824
#Sta/Elev= 30
       0  2195.6    10.2 2191.92    34.2 2185.25    78.3 2168.71    98.3 2162.27
   150.3  2147.1   162.3 2145.67   170.4 2141.41   178.7 2135.52   186.4 2132.65
   206.4  2130.8   290.1 2129.84   310.5 2130.71   326.5 2128.12   334.5 2126.69
   342.5 2127.47   350.5 2127.81   362.5 2130.39   378.5 2131.69   386.6  2134.4
   401.5 2142.27   420.9 2143.75   426.2 2147.56   438.1 2160.25   442.4  2163.9
   515.7 2211.08   540.4 2225.63   571.3  2242.3   618.6 2266.05   639.3  2275.6
#Mann= 5, -1 ,  0
       0     0.1       0     100    0.05       0     290     0.1       0
   326.5   0.045       0   342.5     0.1       0
Bank Sta=326.5,342.5
XS Rating Curve= 0 ,0
Exp/Cntr(USF)=0,0
Exp/Cntr=0.3,0.1

Type RM Length L Ch R = 1 ,500     ,82.6,82.6,82.6
BEGIN DESCRIPTION:
Structure
END DESCRIPTION:
XS GIS Cut Line= 3
2312093.85707791728673.8997902392311790.66286312728719.595868113
2311620.02442802728833.444819566
#Sta/Elev= 30
       0 2140.13    34.1 2138.37    53.6 2135.14    70.5 2131.08    78.6 2129.94
   155.3 2126.85   183.7 2126.53     208 2127.56   212.1 2127.27215.5235 2125.49
   220.1 2123.96   224.2 2124.73225.87322125.702   228.2 2127.05   232.3 2127.69
   272.7 2126.08   296.1 2129.61   305.1 2131.58   314.4 2137.82   318.2 2139.27
   335.5 2139.67   338.5 2141.32     347 2151.35   352.8 2157.03   393.2 2184.25
   413.4 2196.02   444.2 2215.37   468.8 2229.54   496.9 2244.38   511.8 2253.21
#Mann= 4, -1 ,  0
       0    0.06       0     140     0.1       0215.5235   0.045       0
225.8732     0.1       0
Bank Sta=215.5235,225.8732
XS Rating Curve= 0 ,0
Exp/Cntr(USF)=0,0
Exp/Cntr=0.3,0.1

Type RM Length L Ch R = 1 ,418     ,368.1,368.1,368.1
XS GIS Cut Line= 4
2312067.44848783728611.3531295352311939.64350524728601.368110835
2311699.77100347728675.8584318952311592.47760525728752.398945277
#Sta/Elev= 30
       0 2137.48    59.5 2132.07     136 2127.27     157 2126.95     182 2124.98
   213.9 2124.14   218.8 2123.25     224 2122.53233.08942123.173   253.3  2125.1
   258.7 2124.95   271.4  2123.2   341.7  2123.5   345.4 2124.45   354.5 2130.16
   360.9    2133   366.4 2133.72   374.8 2133.46   376.9 2134.16   379.4 2135.47
   382.9 2139.72   385.8 2144.65   388.6 2150.25   391.5 2154.49   394.4 2157.78
   398.5 2161.09   431.6 2182.98   467.3 2204.54   494.7    2224   511.2 2233.33
#Mann= 6, -1 ,  0
       0    0.06       0     120     0.1       0  218.19    0.06       0
   218.8   0.045       0233.0894    0.06       0  308.19     0.1       0
#XS Ineff= 1 ,-1
   255.4     409 2127.05
Permanent Ineff=
       T
Bank Sta=218.8,233.0894
XS Rating Curve= 0 ,0
Exp/Cntr(USF)=0,0
Exp/Cntr=0.3,0.1

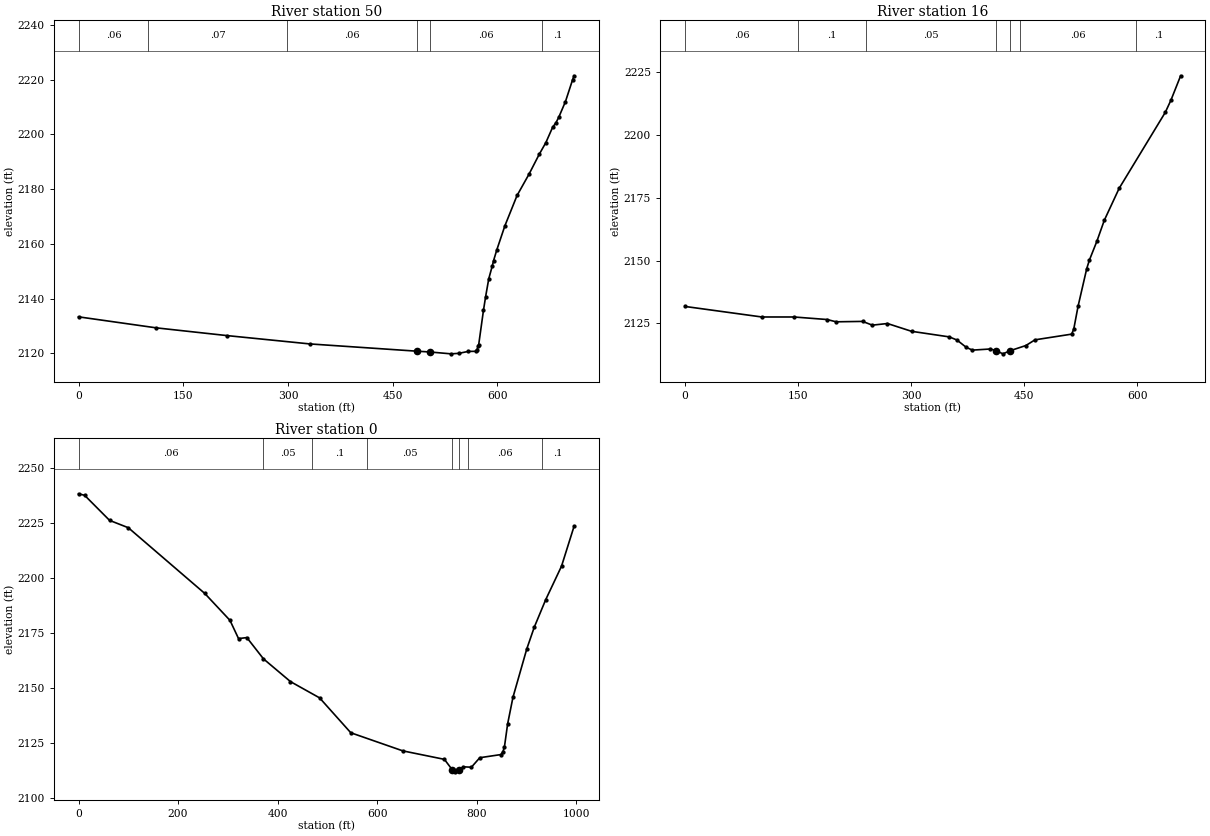
Type RM Length L Ch R = 1 ,50      ,33.8,33.8,33.8
BEGIN DESCRIPTION:
Structure
END DESCRIPTION:
XS GIS Cut Line= 6
2312054.93915569728566.8755041462311817.99876075728535.761956507
2311681.31927257728509.1094563112311602.72856686728483.823750997
2311537.80580998728451.7040712742311440.62243127728599.023111976
#Sta/Elev= 30
       0 2133.34   111.5 2129.31   212.6 2126.49   331.4 2123.44485.26822120.779
502.76822120.509   533.4 2119.82   544.8    2120   558.2 2120.71   568.7 2120.74
   570.3 2121.14   572.7  2122.6   573.2 2123.23     580 2135.72   583.1 2140.74
   587.6 2147.28   592.7 2152.01   594.5 2153.91   599.2 2157.89   610.7 2166.62
   628.1 2177.68   645.4 2185.55   659.8  2192.7   669.4 2197.03     679 2202.58
   683.8 2204.26   687.8 2206.24   697.4 2211.97   707.7 2220.02   709.9 2221.42
#Mann= 6, -1 ,  0
       0    0.06       0     100    0.07       0     299    0.06       0
485.2682   0.045       0502.7682    0.06       0  663.44     0.1       0
Bank Sta=485.2682,502.7682
XS Rating Curve= 0 ,0
Exp/Cntr(USF)=0,0
Exp/Cntr=0.3,0.1

Type RM Length L Ch R = 1 ,16      ,15.9,15.9,15.9
XS GIS Cut Line= 5
2312000.73204975728458.4612922612311616.39651568 728448.28708407
2311545.98369037728429.1359087222311527.26004183728454.583665854
2311428.15955327 728591.21093359
#Sta/Elev= 30
       0 2131.73     102 2127.54   144.6 2127.54   188.6 2126.53   200.6 2125.62
   235.7 2125.78   248.6 2124.29   268.7 2124.94   300.7 2121.84   350.8 2119.62
     361 2118.37   373.3 2115.45   381.5 2114.36   405.4 2114.81413.22182114.094
     422 2112.88431.23182114.101   452.4 2116.18   464.5 2118.45   513.2 2120.72
     516 2122.78   521.7 2131.83   533.2 2146.79   536.7 2150.16   546.6 2157.62
   556.5    2166   576.2 2178.71   637.4 2208.91   644.9 2213.75   657.8 2223.48
#Mann= 7, -1 ,  0
       0    0.06       0     150     0.1       0     240    0.05       0
413.2218   0.045       0431.2318    0.05       0  444.47    0.06       0
  599.03     0.1       0
Bank Sta=413.2218,431.2318
XS Rating Curve= 0 ,0
Exp/Cntr(USF)=0,0
Exp/Cntr=0.3,0.1

Type RM Length L Ch R = 1 ,0       ,,,
XS GIS Cut Line= 4
2312307.93701956728224.5452304672311644.97578725728425.215138944
 2311546.4886906728420.9755302692311424.61980542728585.619587063
#Sta/Elev= 30
       0 2238.25    12.3 2237.55    62.4 2226.18   100.1 2222.84   253.8    2193
   304.4 2180.79   321.6 2172.52   338.3 2172.98   371.7 2163.32     426 2152.99
   484.5 2145.61   547.2 2129.78   651.7 2121.56   735.3 2117.71     751 2113.01
   757.5 2112.04   764.6 2112.99   773.5 2114.32   789.6 2114.14   806.4 2118.45
   848.9 2119.88   853.1 2121.26     856 2123.42   862.4 2133.82   873.1 2145.88
     901 2167.93     916 2177.74   938.9 2190.18   970.7 2205.39   996.1 2223.63
#Mann= 8, -1 ,  0
       0    0.06       0     370    0.05       0     470     0.1       0
     580    0.05       0     751   0.045       0   764.6    0.05       0
  782.67    0.06       0  931.24     0.1       0
Bank Sta=751,764.6
XS Rating Curve= 0 ,0
Exp/Cntr=0.3,0.1
LCMann Table=0

Chan Stop Cuts=-1
Use User Specified Reach Order=0
Composite Channel Slope=5